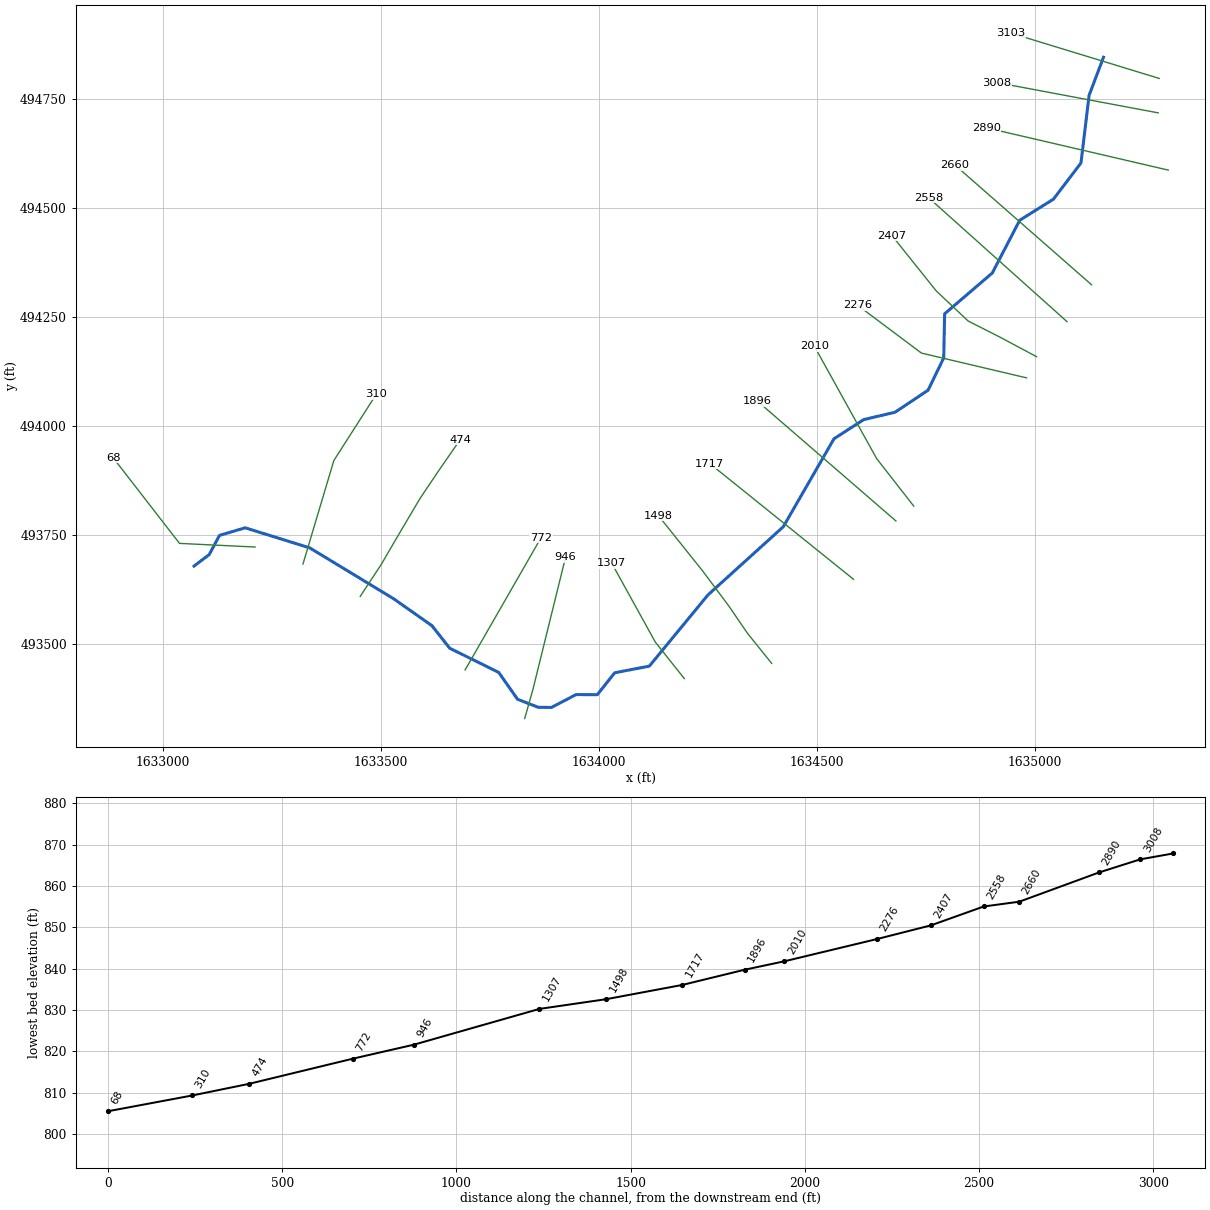
--- GraveCkT4.prj (project) ---

Proj Title=GraveCkT4
Current Plan=p01
Default Exp/Contr=0,0
English Units
Geom File=g01
Flow File=f01
Plan File=p01
BEGIN DESCRIPTION:
---------- MODELED AS PART OF WVEM CTP PROGRAM, 2025----------
Stream Name: Grave Creek Tributary 4
Flood Zone: AFH
Marshall County, WV
HEC-RAS Version: RAS 6.6
Vertical Datum: NAVD88
Projection: NAD 1983 StatePlane West Virginia N FIPS 4701 (US Feet)
Terrain: 1-meter West Virginia FEMA R3 South Central (collected 2018-2019)
Land Use: 2024 NLCD
Hydrologic Method:
Duda et al., "Estimation of magnitude and frequency of floods for rural, unregulated streams in and near Virginia and West Virginia." September 8, 2025.
Additional Model Notes:
None
END DESCRIPTION:
DSS File=dss
DSS Export Rating Curves= 0
DSS Export Rating Curve Sorted= 0
DSS Export Volume Flow Curves= 0
DXF OffsetX= 0
DXF OffsetY= 0
DXF ScaleX= 0
DXF ScaleY= 0

--- GraveCkT4.p01 (plan) ---

Plan Title=Floodplain
Program Version=6.60
Short Identifier=Floodplain
Geom File=g01
Flow File=f01
Subcritical Flow
K Sum by GR= 0
Std Step Tol= 0.01
Critical Tol= 0.01
Num of Std Step Trials= 20
Max Error Tol= 0.3
Flow Tol Ratio= 0.001
Split Flow NTrial= 30
Split Flow Tol= 0.02
Split Flow Ratio= 0.02
Log Output Level= 0
Friction Slope Method= 1
Unsteady Friction Slope Method= 2
Unsteady Bridges Friction Slope Method= 1
Parabolic Critical Depth
Global Vel Dist= 0 , 0 , 0
Global Log Level= 0
CheckData=False
Encroach Param=-1 ,0,0, 0
Flow Ratio Tolerance=0.1
Flow Ratio Min Ratio=0.5
Flow Ratio Max Ratio=4
Flow Ratio Max Iterations= 10
Computation Interval=0.1SEC
Output Interval=1SEC
Instantaneous Interval=Max Profile
Mapping Interval=1HOUR
Computation Time Step Use Courant=        0
Computation Time Step Use Time Series=    0
Computation Time Step Count To Double=0
Computation Time Step Max Doubling=0
Computation Time Step Max Halving=0
Computation Time Step Residence Courant=0
Run HTab= 0
Run UNet= 0
Run Sediment= 0
Run PostProcess= 0
Run WQNet= 0
Run RASMapper=-1
UNET Theta= 0
UNET Theta Warmup= 0
UNET ZTol= 0
UNET ZSATol= 0
UNET MxIter= 0
UNET Max Iter WO Improvement= 0
UNET MaxInSteps= 0
UNET DtIC= 0
UNET DtMin= 0
UNET MaxCRTS= 0
UNET WFStab= 0
UNET SFStab= 0
UNET WFX= 1
UNET SFX= 1
UNET Gravity=32.17405
UNET 1D Methodology=Finite Difference
UNET DSS MLevel= 1
UNET Pardiso=0
UNET DZMax Abort= 0
UNET Use Existing IB Tables= 0
UNET Froude Reduction=False
UNET Froude Limit= 0
UNET Froude Power= 0
UNET D1 Cores= 0
UNET WindReference=Eulerian
UNET WindDragFormulation=Hsu (1988)
UNET D2 Coriolis=0
UNET D2 Cores= 0
UNET D2 Theta= 1
UNET D2 Theta Warmup= 1
UNET D2 Z Tol= 0.01
UNET D2 Volume Tol= 0.01
UNET D2 Max Iterations= 20
UNET D2 Advanced Convergence=0
UNET D2 WS Max Tol=0.15
UNET D2 WS RMS Tol=0.002
UNET D2 WS Stall Tol=1
UNET D2 Equation= 0
UNET D2 RampUpFraction=0.1
UNET D2 TimeSlices= 1
UNET D2 Turbulence Formulation=Non-Conservative (original)
UNET D2 Eddy Viscosity=0.3
UNET D2 Transverse Eddy Viscosity=0.1
UNET D2 Smagorinsky Mixing=0
UNET D2 BCVolumeCheck=0
UNET D2 Cores=0
UNET D2 SolverType=PARDISO (Direct)
UNET D2 Minimum Iterations= 3
UNET D2 Maximum Iterations= 30
UNET D2 Restart Number= 10
UNET D2 Relaxation Coeff=1.3
UNET D2 SOR Precondition Iterations= 10
UNET D2 ILUT Maximum Fill= 8
UNET D2 ILUT Tolerance=1E-08
UNET D2 Convergence Tolerance=0.00001
PS Theta= 1
PS WS Tol= 0.01
PS Volume Tol= 0.01
PS Max Iterations= 20
PS Equation= 0
PS Advance Time Step=-1
PS Target Courant=0.9
PS Time Slices= 1
PS Iterate With 2D=0
PS Project Initial WSE from DS=-1
PS Ramp Up Initial WSE from US=-1
PS Cores=0
UNET D1D2 MaxIter= 0
UNET D1D2 ZTol=0.01
UNET D1D2 QTol=0.1
UNET D1D2 MinQTol=1
DSS File=dss
Write IC File= 0
Write IC File at Fixed DateTime=0
Write IC File at Sim End=0
Echo Input=False
Echo Parameters=False
Echo Output=False
Write Detailed= 0
HDF Write Warmup=0
HDF Write Time Slices=0
HDF Flush=0
HDF Compression= 1
HDF Chunk Size= 1
HDF Spatial Parts= 1
HDF Use Max Rows=0
HDF Fixed Rows= 1
Calibration Method= 0
Calibration Iterations= 20
Calibration Max Change=0.05
Calibration Tolerance=0.2
Calibration Maximum=1.5
Calibration Minimum=0.5
Calibration Optimization Method= 1
WQ AD Non Conservative
WQ ULTIMATE=-1
WQ Max Comp Step=1HOUR
WQ Output Interval=15MIN
WQ Output Selected Increments= 0
WQ Create Restart=0
WQ Fixed Restart=0
WQ System Summary=0
WQ Write To DSS=0
Sorting and Armoring Iterations= 10
XS Update Threshold= 0.02
Bed Roughness Predictor= 0
Processes Affected by Predictor=Sediment Only
Hydraulics Update Threshold= 0.02
Energy Slope Method= 1
Volume Change Method= 1
Sediment Retention Method= 0
Sediment TS Multiplier= 1
Warm Up Method= 0
XS Weighting Method= 0
Number of US Weighted Cross Sections= 1
Number of DS Weighted Cross Sections= 1
Upstream XS Weight=0
Main XS Weight=1
Downstream XS Weight=0
Number of DS XS's Weighted with US Boundary= 1
Upstream Boundary Weight= 1
Weight of XSs Associated with US Boundary= 0
Number of US XS's Weighted with DS Boundary= 1
Downstream Boundary Weight= 0.5
Weight of XSs Associated with DS Boundary= 0.5
Percentile Method= 0
Sediment Output Level= 3
Mass or Volume Output= 0
Output Increment Type= 1
Profile and TS Output Increment= 1
Transport Output Increment 1
XS Output Flag= 0
XS Output Increment= 10
Read HDF5 Sediment Hotstart= 0
Sediment Hotstart Type= 0
Write Gradation File= 0
Read Gradation Hotstart= 0
Write HDF5 File= 1
Write Binary Output= 1
Write DSS Sediment File= 0
DSS Sediment Output Type= 1
SV Curve= 0
Specific Gage Flag= 0
Subcell Erosion Methods= 0
Subcell Deposition Methods= 0
Advection Scheme= 1
Matrix Solver= 0
Implicit Weighting Factor= 1
Maximum Outer Loop Convergence Iterations= 5
Convergence Maximum Absolute= 0.001
Convergence RMSE= 0.0001
Grain Fractions Max Abs Error= 0.001
Max Subgrid Regions= 1
Max Subgrid Length Scale= 3.402823E+38
Initial Layer Thickness= 3
Min Layer Thickness= 0.1
Max Layer Thickness= 6
Number of Layers= 5

--- GraveCkT4.f01 (steady flow) ---

Flow Title=Flow
Program Version=6.60
Number of Profiles= 1
Profile Names=P100yr
River Rch & RM=GraveCkT4,Main,3103
     675
Boundary for River Rch & Prof#=GraveCkT4,Main            , 1
Up Type= 0
Dn Type= 3
Dn Slope=0.027326
DSS Import GetInterval= 0
DSS Import GetPeak= 0
DSS Import FillOption= 0

--- GraveCkT4.g01 (geometry) ---

Geom Title=Geometry
Program Version=6.60

River Reach=GraveCkT4       ,Main
Reach XY= 30
     1635156.897      494845.098     1635123.823      494757.637
     1635105.245      494602.681     1635041.882      494519.398
     1634964.779      494471.307     1634901.791      494350.198
     1634792.541      494256.728     1634790.482      494155.549
     1634754.592      494081.547     1634678.659      494030.916
     1634606.975      494014.113     1634538.837      493970.177
     1634422.571      493768.413     1634249.999      493612.265
     1634115.314      493448.758      1634036.07      493433.545
     1633996.033      493383.302     1633947.258      493383.468
     1633890.877      493354.037     1633860.454      493354.368
      1633813.13      493372.794     1633769.958      493434.337
     1633657.435       493489.91     1633617.019      493541.349
     1633528.838      493603.351     1633336.529      493719.971
     1633188.467      493765.978     1633129.527      493748.518
     1633106.035      493704.498     1633071.317      493678.311

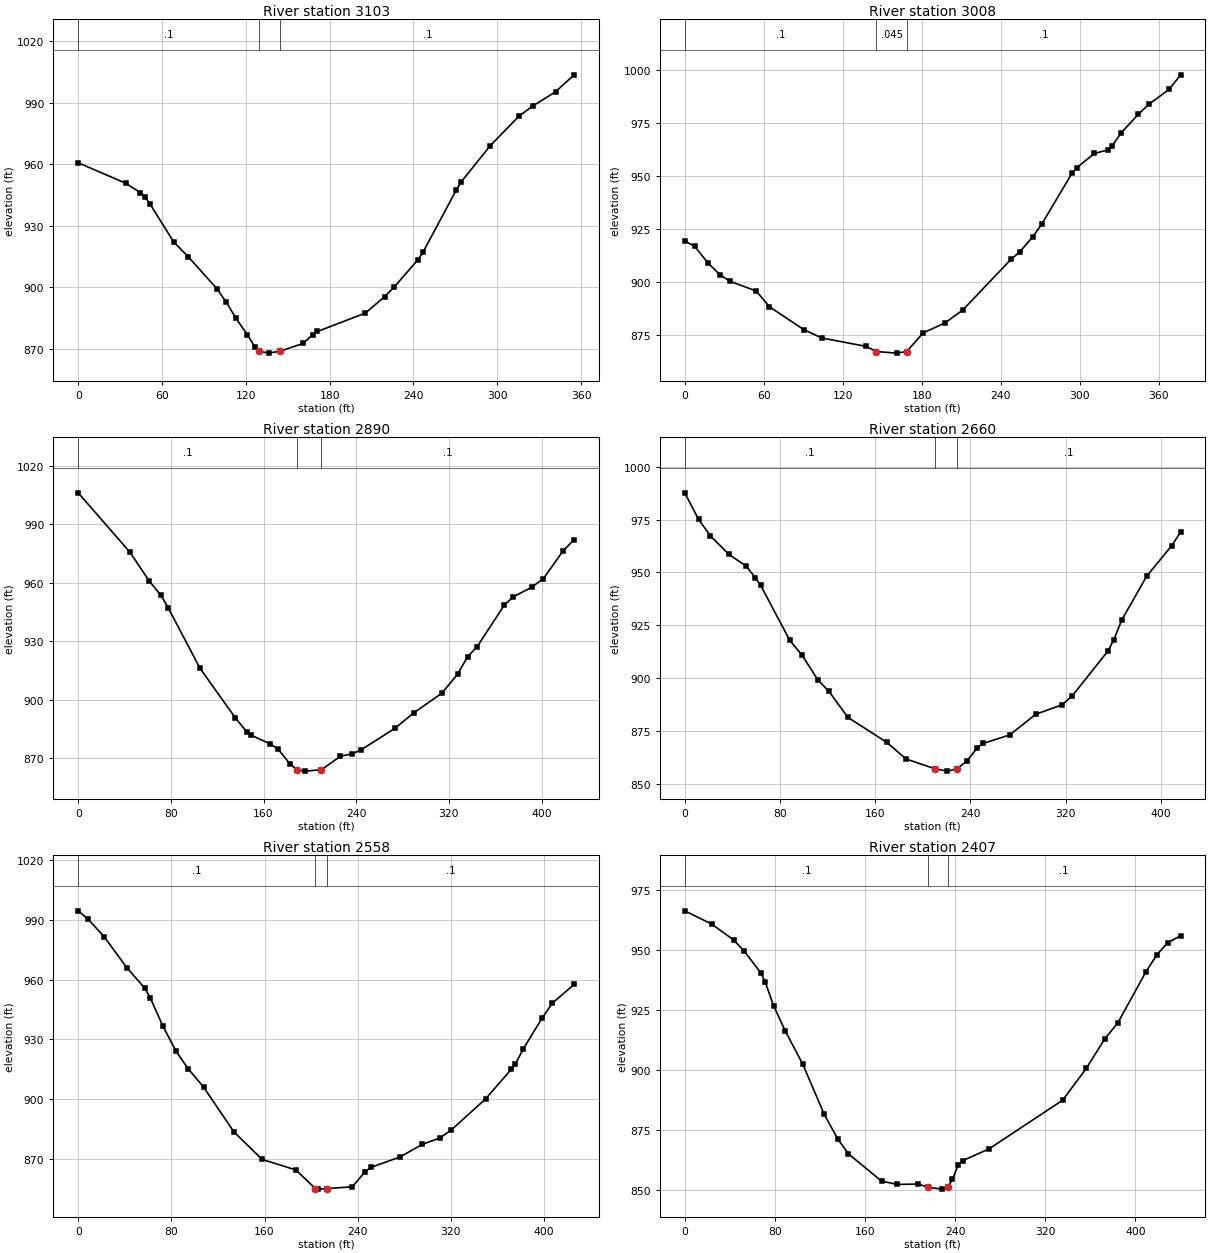
Type RM Length L Ch R = 1 ,3103    ,92.7,95,95.3
XS GIS Cut Line= 2
1635284.61316932  494796.49545311634945.16902922494900.276540808
#Sta/Elev= 30
       0  960.76    34.1  950.72    44.4  946.23    47.8   944.1    51.2  940.84
    68.4   922.1    78.7  914.94    99.2   899.4   106.1  892.62     113  884.81
   121.1  876.88   126.3  871.03  129.52868.8839   136.3  867.88   144.8868.8859
     161  872.61   167.9  876.93   171.3  878.45   205.6  887.42   219.3  895.42
   226.2  900.13   243.3   913.5   246.8  917.08   270.8  947.63   274.2  951.46
   294.8  968.93   315.4  983.41   325.7  988.57   341.8  995.41     355 1003.66
#Mann= 3 ,-1,0
       0      .1       0  129.52    .045       0   144.8      .1       0
Bank Sta=129.52,144.8
XS Rating Curve= 0 ,0
Exp/Cntr=0.3,0.1

Type RM Length L Ch R = 1 ,3008    ,117,118.3,116.2
XS GIS Cut Line= 2
1635282.42311263494717.5199393621634912.05992508494787.057517433
#Sta/Elev= 30
       0  919.36     7.5  916.79    17.6  909.03    26.6  903.48    34.3  900.35
    54.3  895.73    64.3  888.36    90.6  877.47   104.4  873.56   137.7  869.64
  145.71867.1868   161.1  866.45  168.63867.1865   181.1  875.95   197.8  880.71
   211.2  886.73   247.9  910.65   254.6  914.17   264.6  921.41   271.3  927.29
   294.6   951.6     298  953.93   311.3  960.58   321.3  962.22   324.6  963.92
   331.3  970.06   344.7  979.07   352.7  983.77   368.1  990.82   376.8  997.65
#Mann= 3 ,-1,0
       0      .1       0  145.71    .045       0  168.63      .1       0
Bank Sta=145.71,168.63
XS Rating Curve= 0 ,0
Exp/Cntr(USF)=0,0
Exp/Cntr=0.3,0.1

Type RM Length L Ch R = 1 ,2890    ,231.4,229.2,220.6
XS GIS Cut Line= 2
1635305.22846512494586.3096186651634888.28112682494683.308634677
#Sta/Elev= 30
       0 1006.15    44.5  975.77    61.3  960.92    71.5  953.46    77.7  947.12
   105.1  916.12   135.5  890.76   145.6   883.4   148.9  881.85   165.8  877.24
   172.5  874.61   182.6  867.14   188.6863.9839   196.1  863.28  209.96863.9847
   226.4  870.92   236.5  872.17   244.4  874.26   273.6  885.33   289.7   893.2
     314  903.33   327.5  913.02   336.1  921.98   344.3  927.07   367.9  948.55
   375.5  952.68   391.5  957.71   401.6   962.1   418.4  976.19   428.1  982.14
#Mann= 3 ,-1,0
       0      .1       0   188.6    .045       0  209.96      .1       0
Bank Sta=188.6,209.96
XS Rating Curve= 0 ,0
Exp/Cntr(USF)=0,0
Exp/Cntr=0.3,0.1

Type RM Length L Ch R = 1 ,2660    ,100.7,102.1,102.8
XS GIS Cut Line= 2
1635129.38741758494323.4404565841634816.07631345 494597.97931307
#Sta/Elev= 30
       0  987.62    11.6  975.12    21.6  967.27    37.1  958.57    51.5  953.08
    59.4   947.5    63.8  943.91    88.2  917.99    98.7  910.82   111.7  899.41
   121.2   893.8   137.1  881.56   169.6  869.83   185.9  861.94  210.34857.2692
   220.7  856.19  228.51 857.271     237  860.91   245.6  867.06   250.6  869.25
   273.1  873.32   294.9  883.05   316.8  887.48   325.3  891.54   355.6  912.97
   360.4  918.13   367.2  927.61   388.1  948.28   409.1  962.64   416.6  969.12
#Mann= 3 ,-1,0
       0      .1       0  210.34    .045       0  228.51      .1       0
Bank Sta=210.34,228.51
XS Rating Curve= 0 ,0
Exp/Cntr(USF)=0,0
Exp/Cntr=0.3,0.1

Type RM Length L Ch R = 1 ,2558    ,150.7,151.3,151.2
XS GIS Cut Line= 2
1635073.13644411494238.8171471171634755.86891132 494522.90637583
#Sta/Elev= 30
       0  994.42     8.4  990.28    22.3  981.43    41.7     966    57.2  955.69
    61.8  950.93    72.5  936.96    84.2  923.98    94.3  915.41   107.8  906.02
   133.8  883.67     158   869.9     187  864.62  203.69  855.31   205.9  855.03
   213.5  855.31   235.5   856.2   246.5   863.8   251.5  865.93   276.1  871.07
   295.7  877.49   310.4   880.6   320.3  884.58     350  900.29     372  915.08
   375.5  917.72   382.4   925.4   398.4  940.66   407.2  948.18   425.9  957.53
#Mann= 3 ,-1,0
       0      .1       0  203.69    .045       0   213.5      .1       0
Bank Sta=203.69,213.5
XS Rating Curve= 0 ,0
Exp/Cntr(USF)=0,0
Exp/Cntr=0.3,0.1

Type RM Length L Ch R = 1 ,2407    ,148,154.5,154.2
XS GIS Cut Line= 6
1635003.40637034494158.3567972631634919.37897934494203.237284929
1634846.54021426 494240.131240011634773.32874651494309.205248833
1634726.47779034494367.7714046691634671.81746659494436.097711593
#Sta/Elev= 30
       0  966.37    23.9  960.86    43.3  954.28      53  949.49    67.6  940.47
    71.5  936.61    78.9   926.8    89.4  916.18   104.8  902.46   123.5  881.92
   135.7  871.44   145.3  865.15   174.7  853.79   188.8  852.44   207.4  852.58
  215.71851.2306   228.3  850.47  233.35  851.23   237.6  854.48   242.5  860.38
   246.8  862.34   270.1  867.24   335.4  887.51   356.4  900.76   372.8  913.05
   384.4  919.71   409.3  940.96     419  948.07   428.7  953.13   440.1  955.97
#Mann= 3 ,-1,0
       0      .1       0  215.71    .045       0  233.35      .1       0
Bank Sta=215.71,233.35
XS Rating Curve= 0 ,0
Exp/Cntr(USF)=0,0
Exp/Cntr=0.3,0.1

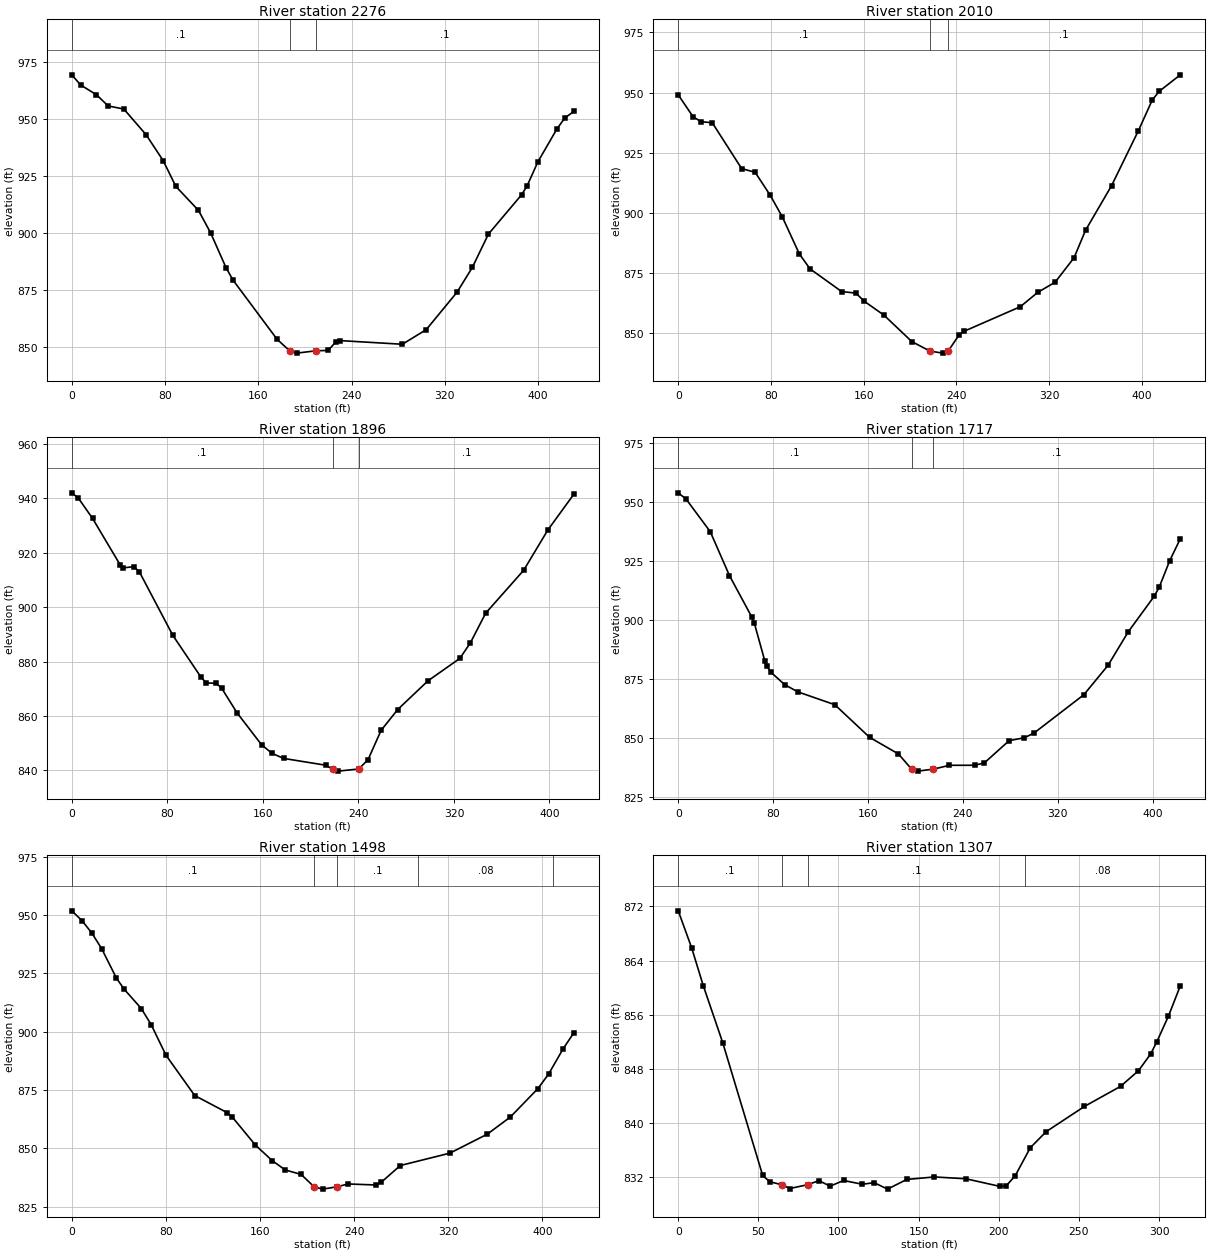
Type RM Length L Ch R = 1 ,2276    ,271,266.1,254.1
XS GIS Cut Line= 3
1634980.57871748494109.7934204281634739.40504901494166.620784463
1634593.01447316494276.326213263
#Sta/Elev= 30
       0  969.49     7.6  965.03    21.1  960.76    31.2  955.82    44.7  954.44
    63.8  943.13    78.4  931.79    89.2   920.5   108.7  909.89   119.2  899.94
   132.3  884.76   138.3  879.27   176.1  853.26  186.83  848.22     193  847.16
   209.8  848.21     220  848.33   226.7  852.23   230.1  852.67   283.6  851.06
   304.1   857.5   330.6  874.01   343.6  884.82   357.4  899.47   385.8  916.72
   390.5  920.57   399.8  931.19   416.2  945.73     423  950.57   430.7  953.38
#Mann= 3 ,0,0
       0      .1       0  186.83    .045       0   209.8      .1       0
Bank Sta=186.83,209.8
XS Rating Curve= 0 ,0
Exp/Cntr(USF)=0,0
Exp/Cntr=0.3,0.1

Type RM Length L Ch R = 1 ,2010    ,109.8,114.4,116.9
XS GIS Cut Line= 3
1634721.65378523493815.7937700551634636.63438102493924.660080328
1634493.55294466494182.828758976
#Sta/Elev= 30
       0  949.08    12.8  940.01    19.6  937.95    29.4  937.49    54.7  918.46
    66.4   916.9    79.4  907.34    89.8  898.41   104.4  883.09   113.7  876.79
     141  867.36   153.4   866.7   160.2  863.44   177.5  857.57   201.6  846.56
  217.15842.6353   228.2  841.77  232.97842.6364   242.5  849.39   246.5  850.81
   295.2  861.05   310.2  866.99   325.3  871.26   341.6  881.41   351.5   892.8
     374  911.38   397.1  934.17   409.2  947.06   415.3  950.64   433.3  957.41
#Mann= 3 ,-1,0
       0      .1       0  217.15    .045       0  232.97      .1       0
Bank Sta=217.15,232.97
XS Rating Curve= 0 ,0
Exp/Cntr(USF)=0,0
Exp/Cntr=0.3,0.1

Type RM Length L Ch R = 1 ,1896    ,177,178.9,178.3
XS GIS Cut Line= 2
1634680.84226403493781.6537568761634362.91402355494056.759984229
#Sta/Elev= 30
       0  942.04     5.5   940.1    17.4  932.64    40.4  915.64    42.9  914.44
      52  914.89    56.7  912.91    84.6  889.65     108   874.4   112.5  872.16
     121  872.01   125.4  870.28   138.4  861.15     159  849.37   167.8  846.23
   177.4  844.39   212.5   841.9  218.37840.5078     223  839.72  240.35840.5081
   248.1  843.95     259   854.7   272.9  862.36   298.2   872.9   324.9  881.15
   333.6  886.75   346.6  897.81   378.4  913.57   398.6  928.36   420.4  941.53
#Mann= 3 ,-1,0
       0      .1       0  218.37    .045       0  240.35      .1       0
Bank Sta=218.37,240.35
XS Rating Curve= 0 ,0
Exp/Cntr(USF)=0,0
Exp/Cntr=0.3,0.1

Type RM Length L Ch R = 1 ,1717    ,220,218.5,215.1
XS GIS Cut Line= 2
1634583.75645889493647.8286056331634254.04706206  493913.2550383
#Sta/Elev= 30
       0  953.84     6.6   951.2      27  937.39    43.2  918.79      62  901.28
    64.2   898.6    72.9  882.85    74.6  880.51    78.3  877.82    89.7  872.66
   100.8   869.6     132  864.15   161.3  850.36   185.7  843.29  196.73836.8866
     202  836.04  215.19836.8871   228.7  838.51   249.8  838.52     258  839.49
     279  848.94   291.9  850.18     300  852.17     342  868.39   362.4  880.85
   379.3  894.93   401.4  910.14   405.6     914   414.3  925.04   423.3  934.42
#Mann= 3 ,-1,0
       0      .1       0  196.73    .045       0  215.19      .1       0
Bank Sta=196.73,215.19
XS Rating Curve= 0 ,0
Exp/Cntr(USF)=0,0
Exp/Cntr=0.3,0.1

Type RM Length L Ch R = 1 ,1498    ,191,191.5,192.4
XS GIS Cut Line= 6
1634395.97681092493455.0219178351634340.39654151493524.142186418
1634297.76604934493586.4471799281634237.92725825493666.638620585
1634191.07498975 493725.203792171634136.41400984   493793.529771
#Sta/Elev= 30
       0  951.79     8.6  947.64      17  942.32    25.4  935.59      38  922.91
    44.6  918.18    59.1  909.94    67.5  903.02    80.1  889.91   104.5  872.67
   132.3  865.28   136.3  863.54   156.1  851.43   170.4  844.78   181.4   840.8
   194.9  838.89  205.94833.5963   213.2  832.59  225.47833.5954   234.8   834.8
   258.2  834.37   262.9  835.47   279.2   842.7   321.3  847.99     353  856.09
   372.6  863.41     396  875.56   405.3  881.91   417.7  892.79   426.7  899.55
#Mann= 5 ,-1,0
       0      .1       0  205.94    .045       0  225.47      .1       0
  294.25     .08       0  409.25      .1       0
Bank Sta=205.94,225.47
XS Rating Curve= 0 ,0
Exp/Cntr(USF)=0,0
Exp/Cntr=0.3,0.1

Type RM Length L Ch R = 1 ,1307    ,365.1,360.3,350.1
XS GIS Cut Line= 3
1634195.50185846493420.286411274  1634129.151225493503.733886707
1634029.21906402493684.663684768
#Sta/Elev= 30
       0  871.35     8.4  865.87    15.6  860.31    27.8  851.85    52.7  832.26
    57.1  831.33   64.49 830.902    69.7  830.33    80.8   830.9    87.8  831.49
    94.8  830.68   103.2  831.52   114.8  830.96   122.3  831.19   130.6  830.24
   142.6  831.67   159.8  832.04   179.5  831.77     201  830.63   204.8  830.76
   210.3  832.23   219.7  836.36   229.6  838.73   253.5  842.46     276  845.42
   287.2  847.73   294.8  850.21   298.5  851.93   305.9   855.8   313.3  860.27
#Mann= 4 ,-1,0
       0      .1       0   64.49    .045       0    80.8      .1       0
  216.61     .08       0
Bank Sta=64.49,80.8
XS Rating Curve= 0 ,0
Exp/Cntr(USF)=0,0
Exp/Cntr=0.3,0.1

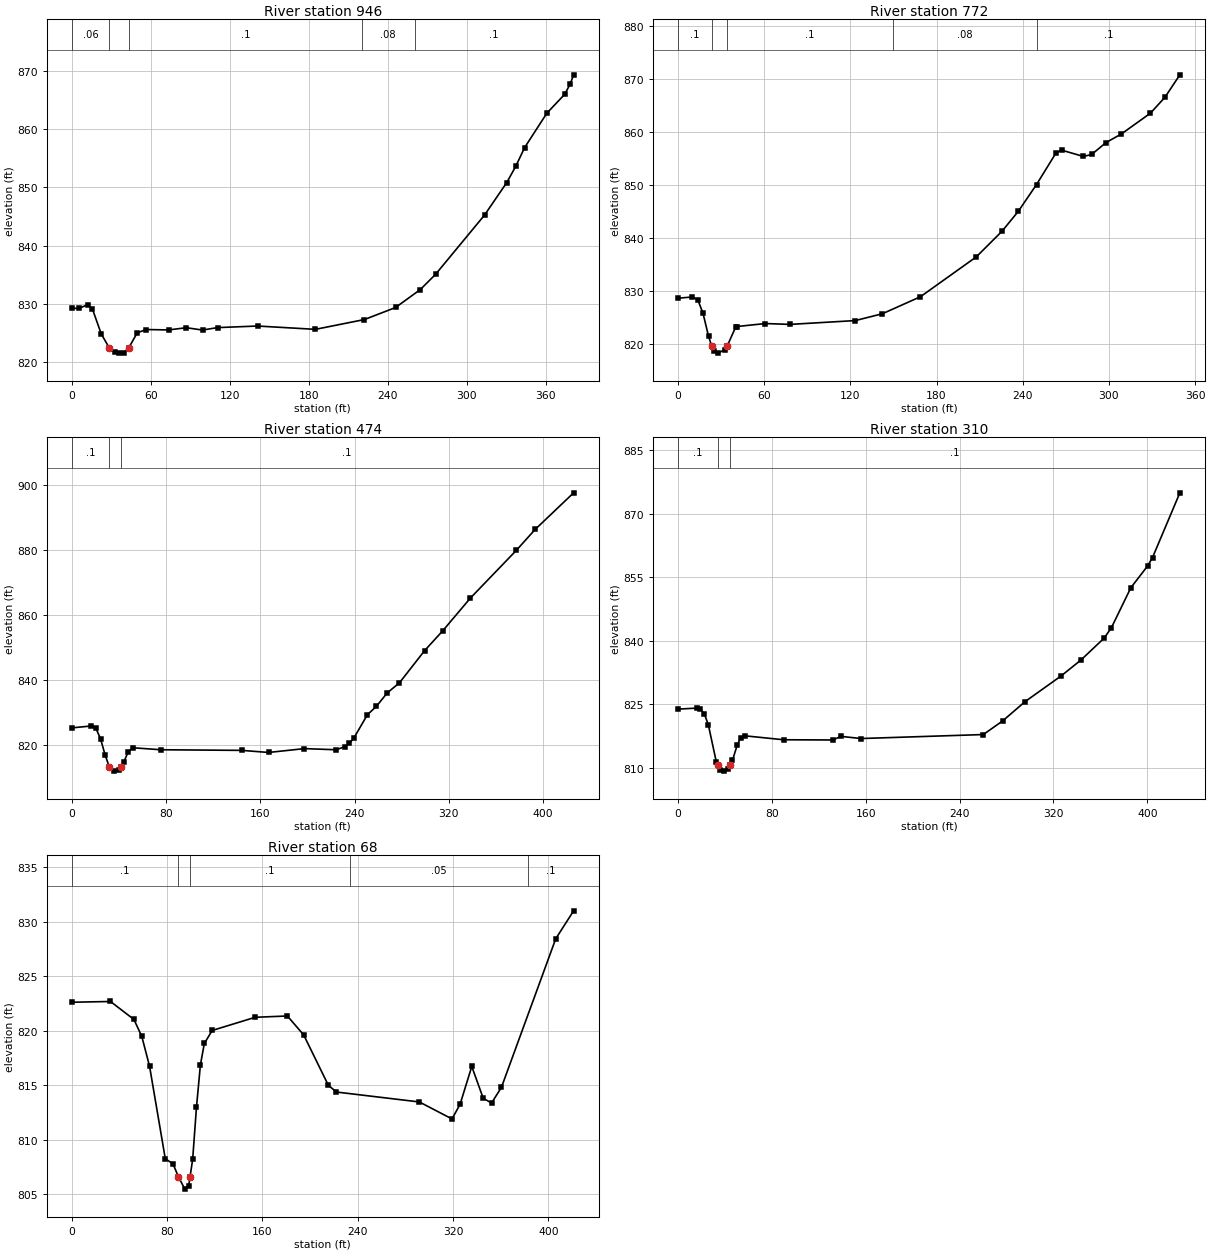
Type RM Length L Ch R = 1 ,946     ,176.7,174.9,171.9
XS GIS Cut Line= 3
 1633829.5433179493328.5817884781633848.64940042493396.236181477
1633923.13174529 493698.02502542
#Sta/Elev= 30
       0  829.29     5.4  829.24    12.2  829.91    15.6  829.21    22.4  824.87
   28.42822.5129    32.6  821.72      36  821.58    39.5  821.63   43.35822.5131
    49.7  825.06    56.5  825.63    73.5  825.56      87  825.94    99.3  825.54
   110.7  825.96   141.1  826.23     185  825.66   222.2  827.34   245.9  829.41
   264.7  832.49   276.3  835.11   313.5  845.28   330.3  850.84   337.1  853.61
   343.9  856.85   360.8  862.76   374.3  865.98   378.5  867.76   381.1  869.33
#Mann= 5 ,-1,0
       0     .06       0   28.42    .045       0   43.35      .1       0
   220.3     .08       0   260.3      .1       0
Bank Sta=28.42,43.35
XS Rating Curve= 0 ,0
Exp/Cntr(USF)=0,0
Exp/Cntr=0.3,0.1

Type RM Length L Ch R = 1 ,772     ,297,297.3,296.1
XS GIS Cut Line= 2
1633692.89595376493440.0033953341633866.85164531493742.985824983
#Sta/Elev= 30
       0  828.56     9.9  828.79    13.7  828.31    17.4  825.74    21.3  821.34
   23.57819.4578      25  818.58    27.9   818.2    32.6  818.86   34.11819.4612
    40.1  823.07    41.1  823.22    60.8  823.78      78  823.62   123.4  824.34
   142.3  825.63   168.8  828.84   207.7  836.36   225.6   841.2   236.9  844.94
   249.6     850   263.3  856.02   267.1  856.49   282.3   855.3     288  855.68
     298  857.92   308.7  859.55   328.9  863.46     339  866.46   349.4   870.7
#Mann= 5 ,-1,0
       0      .1       0   23.57    .045       0   34.11      .1       0
     150     .08       0     250      .1       0
Bank Sta=23.57,34.11
XS Rating Curve= 0 ,0
Exp/Cntr(USF)=0,0
Exp/Cntr=0.3,0.1

Type RM Length L Ch R = 1 ,474     ,162.3,164.3,165.4
XS GIS Cut Line= 6
1633452.30009793493608.6232489081633500.47454226493681.820609066
 1633538.2651491493746.6036159871633589.15218642493832.690057981
1633631.12454343493895.2401297271633681.19235668493967.591034907
#Sta/Elev= 30
       0  825.39    16.6  825.98    20.5  825.25    24.4  822.08    28.3  817.09
   31.99813.2668    36.2  812.12    39.8  812.45   41.45813.2622      44  814.81
      48  818.12    51.9  819.29    75.5  818.68   144.2  818.49     167  817.85
   197.5  819.03   224.2  818.68   231.8  819.61   235.6  820.61   239.5  822.33
   250.9  829.44   258.5  831.99   267.7  836.12   278.1  839.23   299.4  849.09
   314.8  855.18   338.3  865.24   377.3  879.89   393.2  886.29   425.9  897.54
#Mann= 3 ,-1,0
       0      .1       0   31.99    .045       0   41.45      .1       0
Bank Sta=31.99,41.45
XS Rating Curve= 0 ,0
Exp/Cntr(USF)=0,0
Exp/Cntr=0.3,0.1

Type RM Length L Ch R = 1 ,310     ,231.6,241.5,249.7
XS GIS Cut Line= 3
1633321.07779197493682.9319185221633391.87746717493920.287494472
1633488.95641417494071.900898013
#Sta/Elev= 30
       0  823.91    16.2  824.15    19.1  823.94    22.5  822.79    25.9  820.15
    32.7   811.4   34.03810.7173    36.2   809.6    39.6  809.28      43  809.87
   44.58  810.72    46.4  811.81    50.4  815.36    53.3  817.12    56.7  817.62
      90  816.68     132  816.63   138.9  817.48     156  816.97   260.2  817.91
   276.7  821.13   295.7  825.66   326.5  831.74   343.2  835.44   363.2  840.67
   369.4  843.13   385.9  852.54   400.2  857.68   404.4  859.67   427.7  874.94
#Mann= 3 ,-1,0
       0      .1       0   34.03    .045       0   44.58      .1       0
Bank Sta=34.03,44.58
XS Rating Curve= 0 ,0
Exp/Cntr(USF)=0,0
Exp/Cntr=0.3,0.1

Type RM Length L Ch R = 1 ,68      ,,,
XS GIS Cut Line= 3
1633211.01631068493721.9019724941633037.92820875493730.216248133
1632886.02238032493926.259589207
#Sta/Elev= 30
       0  822.62    32.5  822.69    52.2  821.04    58.8  819.48    65.3  816.75
    78.5  808.27      85  807.78   89.51806.6183    94.9  805.47    98.2   805.8
   99.33806.6171   101.5  808.21   104.7     813     108  816.88   111.3  818.84
   117.9  820.03     154  821.24     181  821.36   194.7  819.62   215.4     815
   222.2  814.38   291.8  813.47   319.2  811.91     326  813.26   335.8  816.73
   345.4  813.81   352.4  813.37   360.7  814.81   406.3  828.45   421.3  831.01
#Mann= 5 ,-1,0
       0      .1       0   89.51    .045       0   99.33      .1       0
  233.29     .05       0  383.29      .1       0
Bank Sta=89.51,99.33
XS Rating Curve= 0 ,0
Exp/Cntr(USF)=0,0
Exp/Cntr=0.3,0.1
LCMann Table=0

Chan Stop Cuts=-1
Use User Specified Reach Order=0
Composite Channel Slope=5